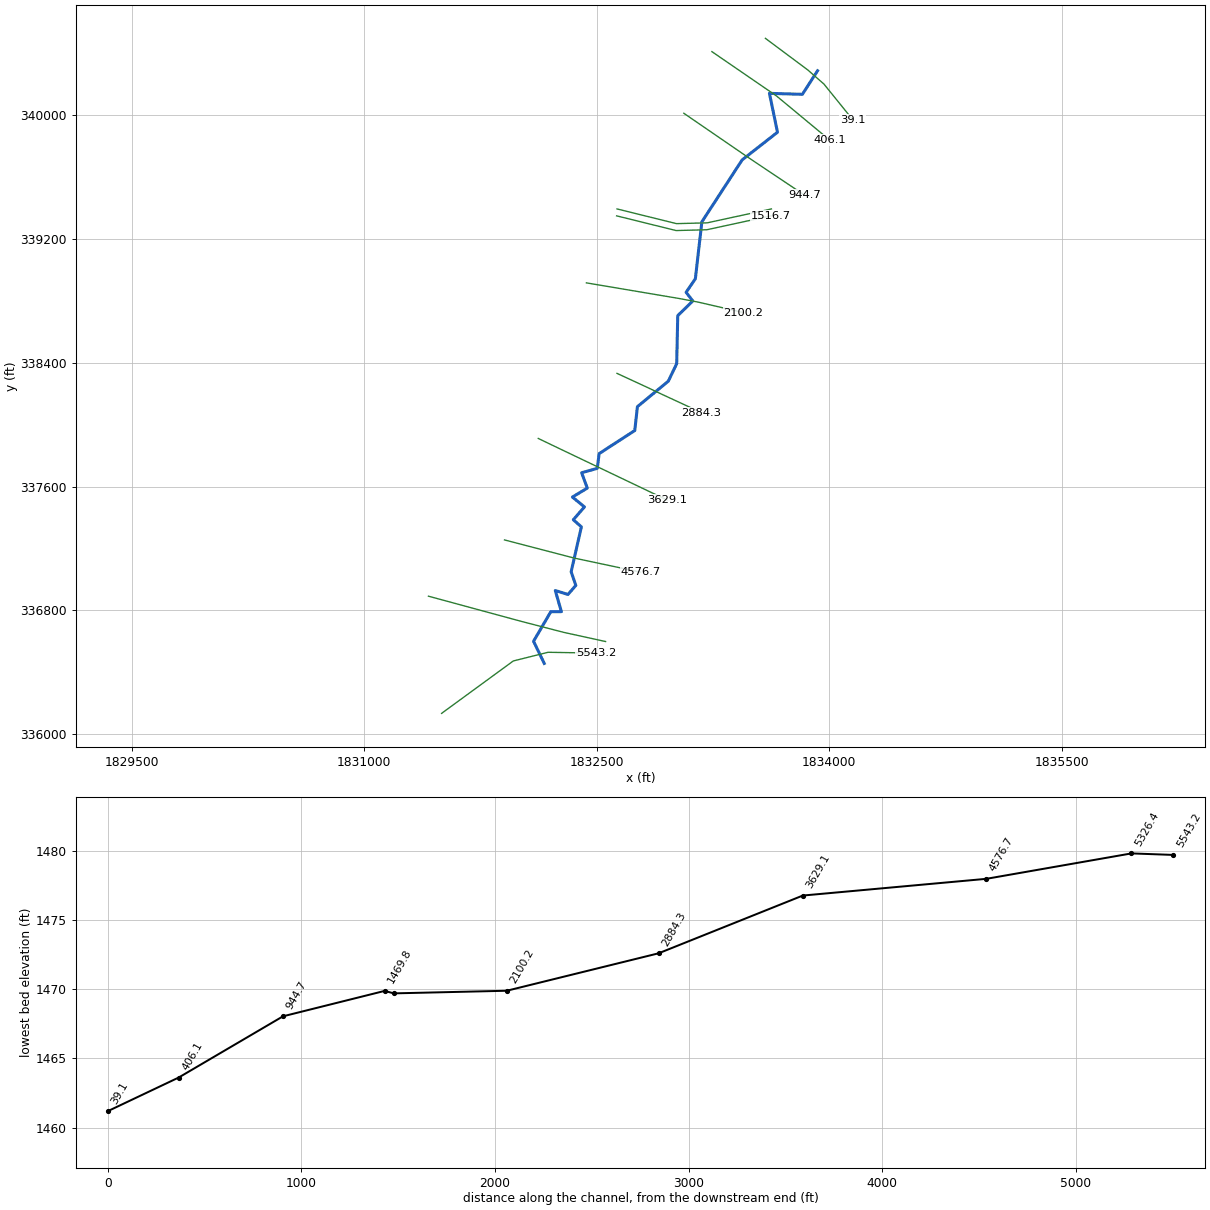
--- CherryRun.prj (project) ---

Proj Title=CherryRun
Current Plan=p01
Default Exp/Contr=0,0
English Units
Geom File=g01
Flow File=f01
Plan File=p01
BEGIN DESCRIPTION:
END DESCRIPTION:
DSS Export Rating Curves= 0
DSS Export Rating Curve Sorted= 0
DSS Export Volume Flow Curves= 0
DXF OffsetX= 0
DXF OffsetY= 0
DXF ScaleX= 0
DXF ScaleY= 0

--- CherryRun.p01 (plan) ---

Plan Title=Floodplain
Program Version=4.00
Geom File=g01
Flow File=f01
K Sum by GR=0
Std Step Tol=0.01
Critical Tol=0.01
Num of Std Step Trials=20
Max Error Tol=0.3
Flow Tol Ratio=0.001
Split Flow NTrial=30
Split Flow Tol=0.02
Split Flow Ratio=0.02
Log Output Level=0
Friction Slope Method=1
Unsteady Friction Slope Method=2
Unsteady Bridges Friction Slope Method=1
Global Log Level=0
CheckData=False
Run HTab=0
Run UNet=0
Run PostProcess=0
UNET Theta=0
UNET Theta Warmup=0
UNET ZTol=0
UNET ZSATol=0
UNET MxIter=0
UNET MaxInSteps=0
UNET DtIC=0
UNET DtMin=0
UNET MaxCRTS=0
UNET WFStab=0
UNET SFStab=0
UNET WFX=0
UNET SFX=0
UNET DSS MLevel=0
UNET DZMax Abort=0
UNET Convert EG Bridges=0
UNET Use Existing IB Tables=0
UNET Froude Limit=0
UNET Froude Power=0
Write IC File=0
Echo Input=False
Echo Output=False
Write Detailed=0

--- CherryRun.f01 (steady flow) ---

Flow Title=NFF Regression Equation
Program Version=4.10
Number of Profiles= 1
Profile Names=P100yr
River Rch & RM=CherryRun,Main            ,5543.2
     655
River Rch & RM=CherryRun,Main            ,5326.4
     964
River Rch & RM=CherryRun,Main            ,2884.3
    1023
River Rch & RM=CherryRun,Main            ,39.1
    1137
Boundary for River Rch & Prof#=CherryRun,Main            , 1
Up Type= 0
Dn Type= 3
Dn Slope=0.0066
DSS Import GetInterval= 0
DSS Import GetPeak= 0
DSS Import FillOption= 0

--- CherryRun.g01 (geometry) ---

Geom Title=USGS 10m DEM
Program Version=4.10

River Reach=CherryRun       ,Main
Reach XY= 30
     1832161.617      336457.141     1832092.498      336600.251
     1832203.912      336791.585     1832272.102      336791.712
     1832232.732      336928.402     1832314.358       336902.76
      1832365.21      336961.261     1832335.118      337049.901
     1832401.079      337339.731     1832349.004      337385.755
     1832420.848      337468.738     1832343.198      337532.524
     1832439.251      337590.409     1832402.693      337689.581
      1832503.55      337717.911     1832515.597      337813.198
     1832745.435      337962.585     1832762.512      338116.854
     1832961.719      338281.342     1833015.793      338394.462
     1833022.649      338705.086     1833119.743      338799.868
     1833076.567      338856.003     1833136.176      338943.529
     1833178.109      339311.277     1833437.892      339711.455
     1833665.918      339890.431     1833613.926      340141.817
     1833826.518      340135.496     1833924.345      340287.889

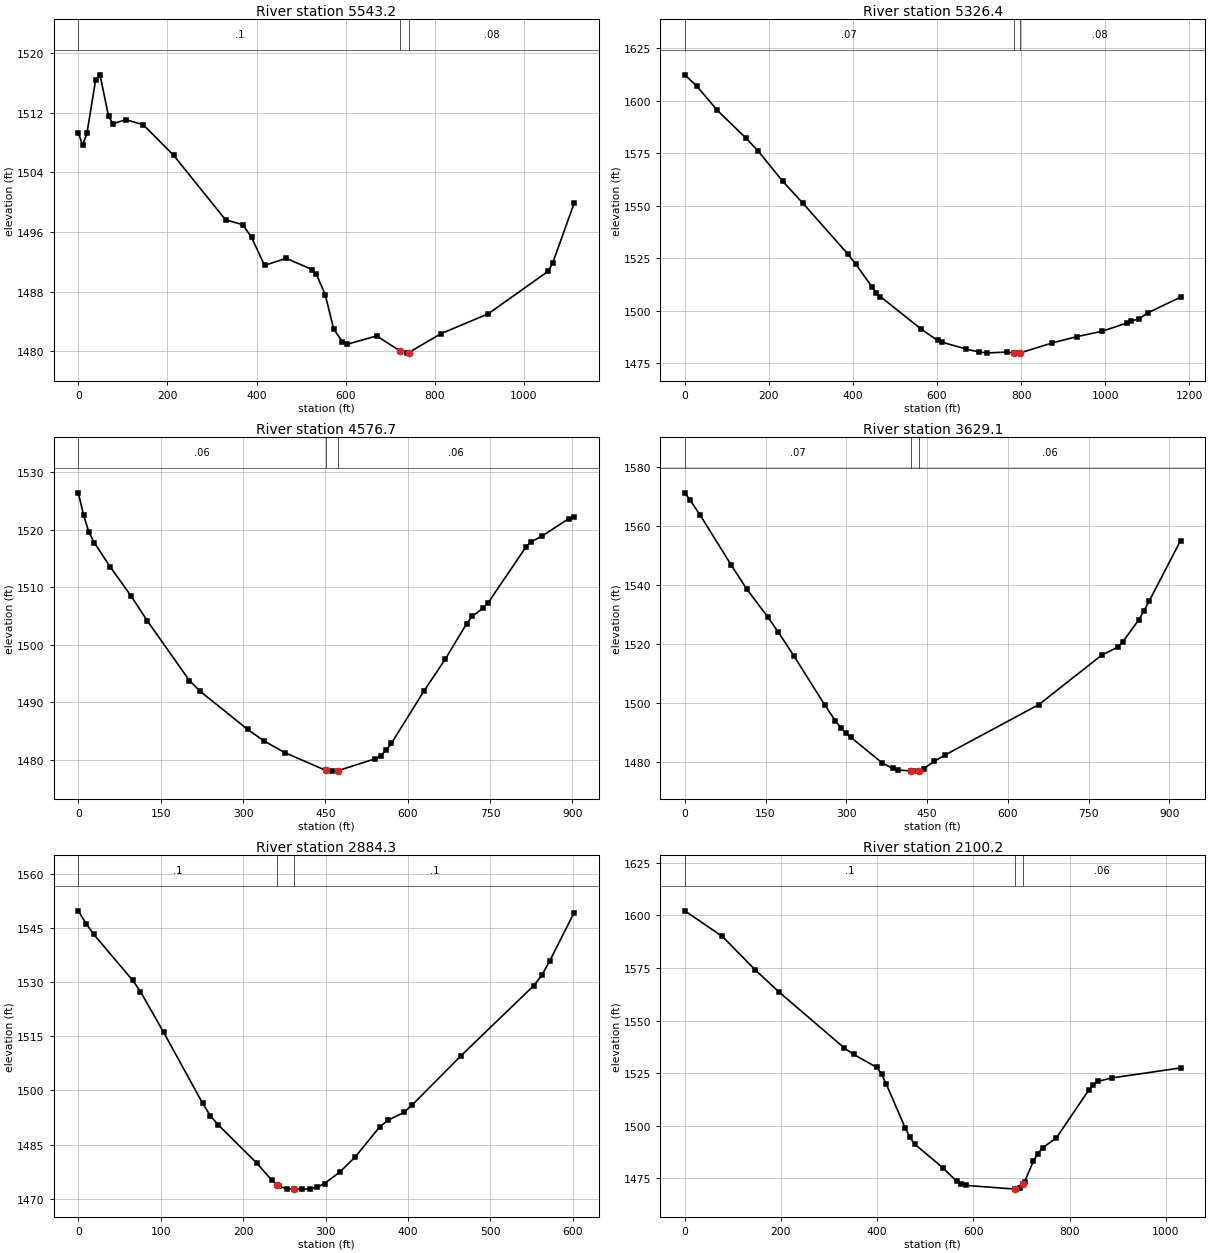
Type RM Length L Ch R = 1 ,5543.2  ,226.2,216.8,204
XS GIS Cut Line= 4
     1831499.415      336134.313     1831962.109      336473.169
     1832186.067      336529.159     1832494.661       336523.95
#Sta/Elev= 30
       0  1509.3     9.7 1507.64    19.4 1509.28    38.9 1516.44    48.6  1517.1
      68 1511.51    77.8 1510.54   106.9 1511.08   145.8 1510.39   213.8  1506.3
   330.5 1497.63   369.4 1496.97   388.8 1495.27     418 1491.51   466.6 1492.46
   524.9 1490.95   534.6  1490.3   554.1 1487.59   573.5 1482.91   592.7 1481.29
   602.4  1480.9   669.7 1482.04   722.9 1479.99     737 1479.73  741.15 1479.79
     814 1482.34   920.1 1485.01  1055.1 1490.74  1064.8 1491.84    1113 1499.87
#Mann= 3 , 0 , 0
       0      .1       0   722.9    .045       0  741.15     .08       0
Bank Sta=722.9,741.15
XS Rating Curve= 0 ,0
Exp/Cntr=0.3,0.1

Type RM Length L Ch R = 1 ,5326.4  ,738.8,749.7,665.1
XS GIS Cut Line= 4
     1831414.809      336891.769     1832013.564      336728.974
      1832287.87      336657.794     1832556.967      336598.766
#Sta/Elev= 30
       0 1612.39    29.1 1606.88    77.6 1595.41   145.4  1582.3   174.5 1576.09
   232.7 1561.72   281.2 1551.19   387.8 1527.03   407.2 1522.12     446 1511.13
   455.7 1508.67   465.4 1506.73   562.3 1491.27   601.1 1485.91   610.8 1485.11
   669.4 1481.77   698.7 1480.42   718.2 1479.93   767.1 1480.35   782.3 1479.97
   786.6 1479.84   797.3 1479.91   874.6 1484.74   933.4 1487.73   992.4 1490.25
  1051.5 1494.16  1061.3  1495.1    1081 1496.17  1100.7 1498.97  1179.4 1506.53
#Mann= 3 , 0 , 0
       0     .07       0   782.3    .045       0   797.3     .08       0
Bank Sta=782.3,797.3
XS Rating Curve= 0 ,0
Exp/Cntr=0.3,0.1

Type RM Length L Ch R = 1 ,4576.7  ,845.7,947.6,894.4
XS GIS Cut Line= 3
     1831905.161      337255.461     1832352.834      337138.574
     1832783.574      337046.948
#Sta/Elev= 30
       0  1526.4     9.6 1522.49    19.3 1519.55    28.9 1517.75    57.8 1513.56
    96.4 1508.41   125.3 1504.19   202.4 1493.74   221.7  1491.9   308.4 1485.25
   337.4  1483.3   375.9 1481.22  451.19 1478.11   462.7    1478   472.5 1478.06
     541 1480.16   550.8  1480.7   560.5  1481.6   570.3 1482.85     629 1491.85
   668.2 1497.45   707.3 1503.65   717.1  1504.9   736.7 1506.32   746.5 1507.29
     815 1516.94   824.8 1517.88   844.3 1518.86   893.3 1521.92   903.1 1522.23
#Mann= 3 , 0 , 0
       0     .06       0  451.19    .045       0   472.5     .06       0
Bank Sta=451.19,472.5
XS Rating Curve= 0 ,0
Exp/Cntr=0.3,0.1

Type RM Length L Ch R = 1 ,3629.1  ,766.9,744.7,754
XS GIS Cut Line= 4
     1832122.959      337911.277     1832270.566      337840.273
     1832566.894      337698.507      1832953.62      337513.493
#Sta/Elev= 30
       0 1571.25     9.6 1568.88    28.9 1563.58    86.7  1546.6   115.6 1538.45
   154.2 1529.11   173.5 1524.01   202.4 1515.98   260.4 1499.12   279.7 1493.88
   289.4 1491.59   299.1 1489.73   308.7 1488.22   366.7 1479.58     386 1477.71
   395.7 1477.18   420.9 1476.84   424.7 1476.79   435.9    1477     444 1477.64
   463.3  1480.1   482.6 1482.19   657.9  1499.4   774.8 1516.22   804.1 1518.86
   813.8 1520.72     843 1528.09   852.8 1531.15   862.5 1534.49     921 1555.06
#Mann= 3 , 0 , 0
       0     .07       0   420.9    .045       0   435.9     .06       0
Bank Sta=420.9,435.9
XS Rating Curve= 0 ,0
Exp/Cntr=0.3,0.1

Type RM Length L Ch R = 1 ,2884.3  ,772.5,784.1,750.5
XS GIS Cut Line= 4
      1832630.88       338331.85     1832827.495      338240.704
     1832926.453      338193.829     1833176.453      338077.943
#Sta/Elev= 30
       0 1549.88     9.4 1546.33    18.8 1543.33      66 1530.57    75.4 1527.47
   103.6 1516.12   150.8 1496.46   160.2 1493.01   169.6  1490.5   216.7 1479.81
     235 1475.02   241.7 1473.79   244.1 1473.35   253.2 1472.69   262.3 1472.67
   271.5 1472.61   280.6 1472.62   289.7 1473.15   298.8 1474.17   317.1  1477.3
     336 1481.52   365.6 1489.84   375.4 1491.69   395.1  1493.9   404.9  1495.9
     464 1509.54   552.6 1529.08   562.4 1531.96   572.2 1535.98   601.8 1549.41
#Mann= 3 , 0 , 0
       0      .1       0   241.7    .045       0   262.3      .1       0
Bank Sta=241.7,262.3
XS Rating Curve= 0 ,0
Exp/Cntr=0.3,0.1

Type RM Length L Ch R = 1 ,2100.2  ,546.6,583.5,551.7
XS GIS Cut Line= 4
     1832433.443      338916.865     1833029.318      338816.225
     1833156.922      338791.919     1833445.985      338725.079
#Sta/Elev= 30
       0 1602.11      78 1589.97   146.2 1574.11   194.9 1563.74   331.4    1537
   350.9 1533.91   399.6  1527.7   409.4 1524.38   419.1 1519.67   458.1 1499.11
   467.9 1494.49   477.6 1491.35   536.1 1480.13   565.3 1473.64   575.1 1472.11
   584.8 1471.68  686.11 1469.92   687.8  1469.9   697.1 1470.52   703.6 1472.53
   706.4  1473.4   724.9 1483.24   734.2 1486.81   743.8 1489.49   772.5 1494.22
   839.5  1516.8   849.1 1519.53   858.6 1521.06   887.3  1522.7  1030.9 1527.47
#Mann= 3 , 0 , 0
       0      .1       0  686.11    .045       0   703.6     .06       0
Bank Sta=686.11,703.6
XS Rating Curve= 0 ,0
Exp/Cntr=0.3,0.1

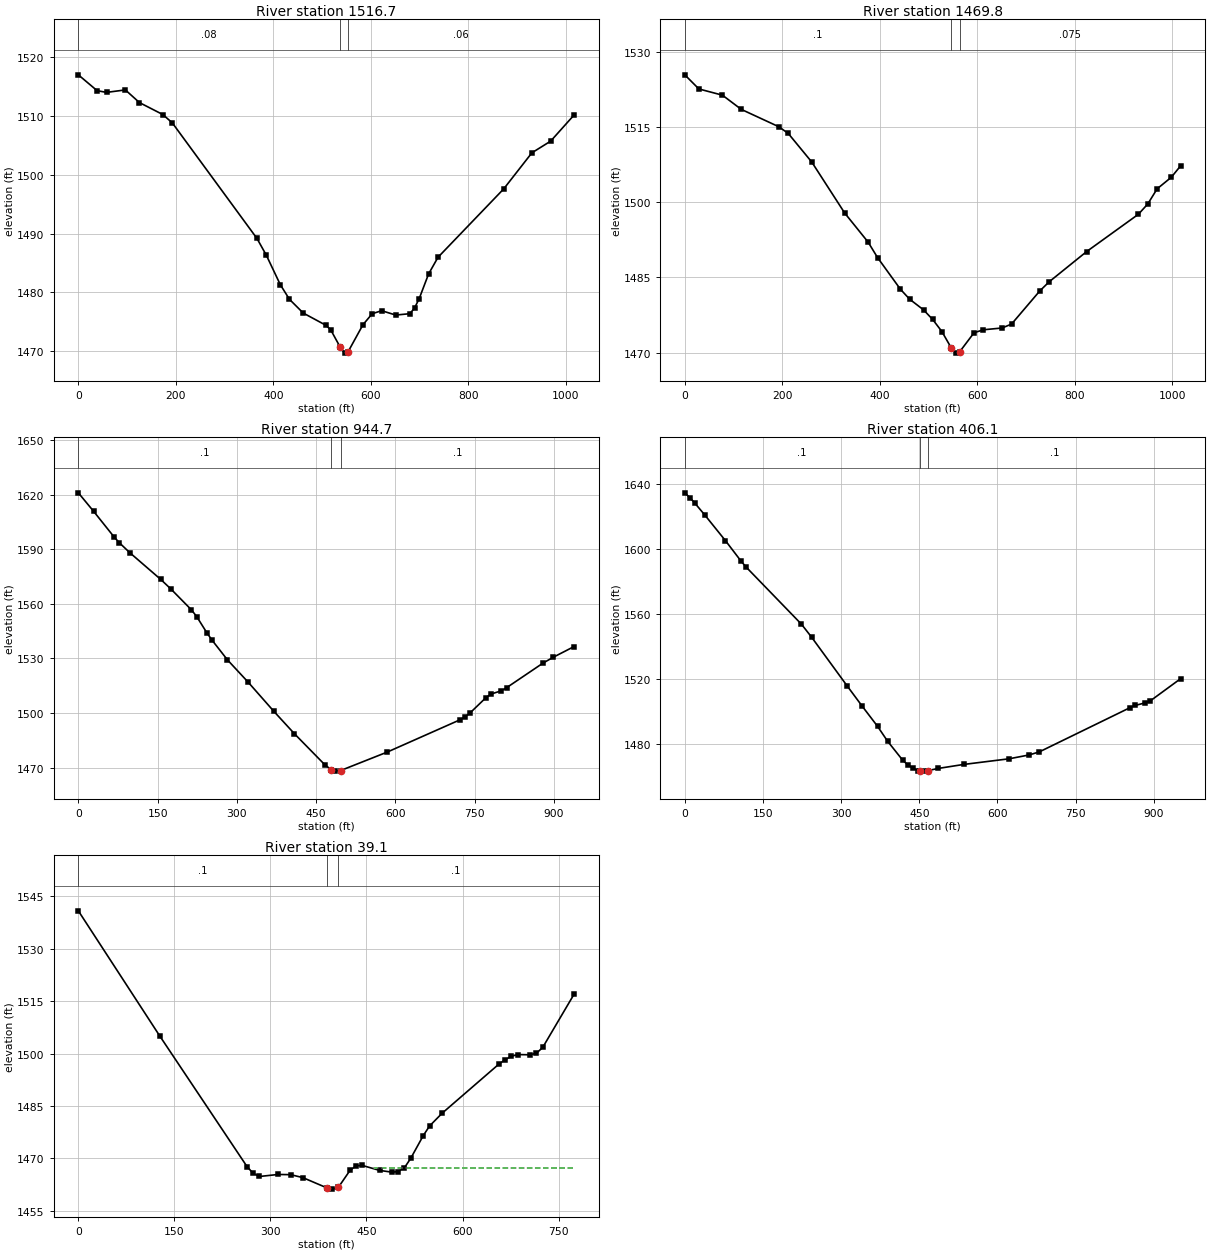
Type RM Length L Ch R = 1 ,1516.7  ,46.9,46.8,47.3
XS GIS Cut Line= 4
     1832628.276      339350.079     1833012.174      339254.954
      1833210.09      339260.163      1833624.37      339350.079
#Sta/Elev= 30
       0 1516.93    38.6 1514.24    57.9 1513.95    96.5 1514.37   125.4 1512.22
   173.6 1510.18   192.9 1508.77   366.6 1489.16   385.9  1486.3   414.4 1481.33
   433.2 1478.84   461.5 1476.51   508.6 1474.41   518.1 1473.63   536.9 1470.79
   546.4 1469.71   553.6 1469.95   584.1 1474.54   603.1  1476.4   622.4 1476.91
   651.3 1476.17   680.2  1476.4   689.8 1477.35   699.5 1478.97   718.7 1483.14
     738 1485.97   872.9 1497.58   930.7  1503.7   969.2 1505.68  1017.4 1510.13
#Mann= 3 , 0 , 0
       0     .08       0   536.9    .045       0   553.6     .06       0
Bank Sta=536.9,553.6
XS Rating Curve= 0 ,0
Exp/Cntr=0.3,0.1

Type RM Length L Ch R = 1 ,1469.8  ,538.9,525.2,509.9
XS GIS Cut Line= 4
      1832630.88      339394.784     1833014.778      339299.659
     1833212.695      339304.868     1833626.974      339394.784
#Sta/Elev= 30
       0 1525.43    28.9 1522.61    77.2 1521.37   115.8 1518.54   192.9 1515.07
   212.2 1513.74   260.5 1508.03     328 1497.86   376.2 1492.04   395.5 1488.96
   442.6 1482.62   461.5 1480.64   489.8 1478.53   508.6 1476.61   527.5  1474.2
   546.4 1470.99   555.8 1469.89   563.9 1470.14   593.5 1473.96   612.8 1474.55
   651.3 1474.91   670.6  1475.7   728.4  1482.3   747.6 1484.12   824.7 1490.17
   930.7  1497.6     950 1499.66   969.2 1502.68   998.2 1504.98  1017.4 1507.27
#Mann= 3 , 0 , 0
       0      .1       0   546.4    .045       0   563.9    .075       0
Bank Sta=546.4,563.9
XS Rating Curve= 0 ,0
Exp/Cntr=0.3,0.1

Type RM Length L Ch R = 1 ,944.7   ,537.9,538.5,538.2
XS GIS Cut Line= 3
     1833061.915      340013.002     1833478.943       339726.24
     1833837.957      339485.658
#Sta/Elev= 30
       0 1621.02    29.2 1610.76    68.1  1596.6    77.9  1593.5    97.3 1588.14
   155.7 1573.49   175.2 1568.15   214.1 1556.68   223.9 1553.04   243.3 1544.05
     253 1540.05   282.2  1529.2   321.2    1517   369.8 1500.98   408.8 1488.64
   467.2 1471.33   478.7 1468.87   486.6 1468.05   496.4 1468.38   584.7 1478.54
   722.2 1496.25     732 1497.88   741.8 1500.17   771.3 1508.42   781.1 1510.42
   800.8 1512.24   810.6 1513.94   879.3 1527.42     899 1530.68   938.3 1536.55
#Mann= 3 , 0 , 0
       0      .1       0   478.7    .045       0   496.4      .1       0
Bank Sta=478.7,496.4
XS Rating Curve= 0 ,0
Exp/Cntr=0.3,0.1

Type RM Length L Ch R = 1 ,406.1   ,369.9,367,364
XS GIS Cut Line= 3
     1833242.905       340411.44     1833659.933      340124.678
     1834002.453      339840.042
#Sta/Elev= 30
       0 1634.67     9.7 1631.69    19.5 1628.25    38.9 1620.84    77.9 1605.32
   107.1 1593.06   116.8 1589.33   223.9 1553.91   243.3 1545.96   311.4 1516.06
   340.6 1503.46   369.8  1491.2   389.3 1481.95   418.5  1470.2   428.2 1467.43
     438 1465.41   447.7    1464   450.6 1463.89   457.4 1463.62   467.2    1464
   486.6 1465.29   535.2 1467.73   622.3  1471.2     661 1473.58   680.4 1475.46
   854.6 1502.66   864.3    1504   883.7  1505.6   893.4 1506.82   951.5 1520.44
#Mann= 3 , 0 , 0
       0      .1       0   450.6    .045       0   467.2      .1       0
Bank Sta=450.6,467.2
XS Rating Curve= 0 ,0
Exp/Cntr=0.3,0.1

Type RM Length L Ch R = 1 ,39.1    ,42.4,39.1,35.8
XS GIS Cut Line= 4
     1833587.957      340497.377     1833861.394       340292.95
     1833965.561      340201.804     1834150.457      339972.637
#Sta/Elev= 30
       0 1540.88   126.8 1505.14   263.4 1467.65   273.1 1465.68   282.9  1464.8
   312.1 1465.38   331.6 1465.32   350.6 1464.48   388.8 1461.49   396.8 1461.18
     406 1461.67   424.4 1466.58   433.7 1467.84   442.9 1467.99   470.6 1466.54
   489.6 1466.04   499.4  1466.2   509.3 1467.32   519.1    1470   538.7 1476.52
   548.5 1479.26   568.2 1482.93   656.5 1496.94   666.3 1498.23   676.1 1499.21
   685.9 1499.72   705.6 1499.65   715.4  1500.1   725.2 1501.76   774.3 1517.05
#Mann= 3 , 0 , 0
       0      .1       0   388.8    .045       0     406      .1       0
#XS Ineff= 2 , 0
                          462.04         1467.09
Permanent Ineff=
       F       F
Bank Sta=388.8,406
XS Rating Curve= 0 ,0
Exp/Cntr=0.3,0.1

Chan Stop Cuts=-1
Use User Specified Reach Order=0
Composite Channel Slope=5